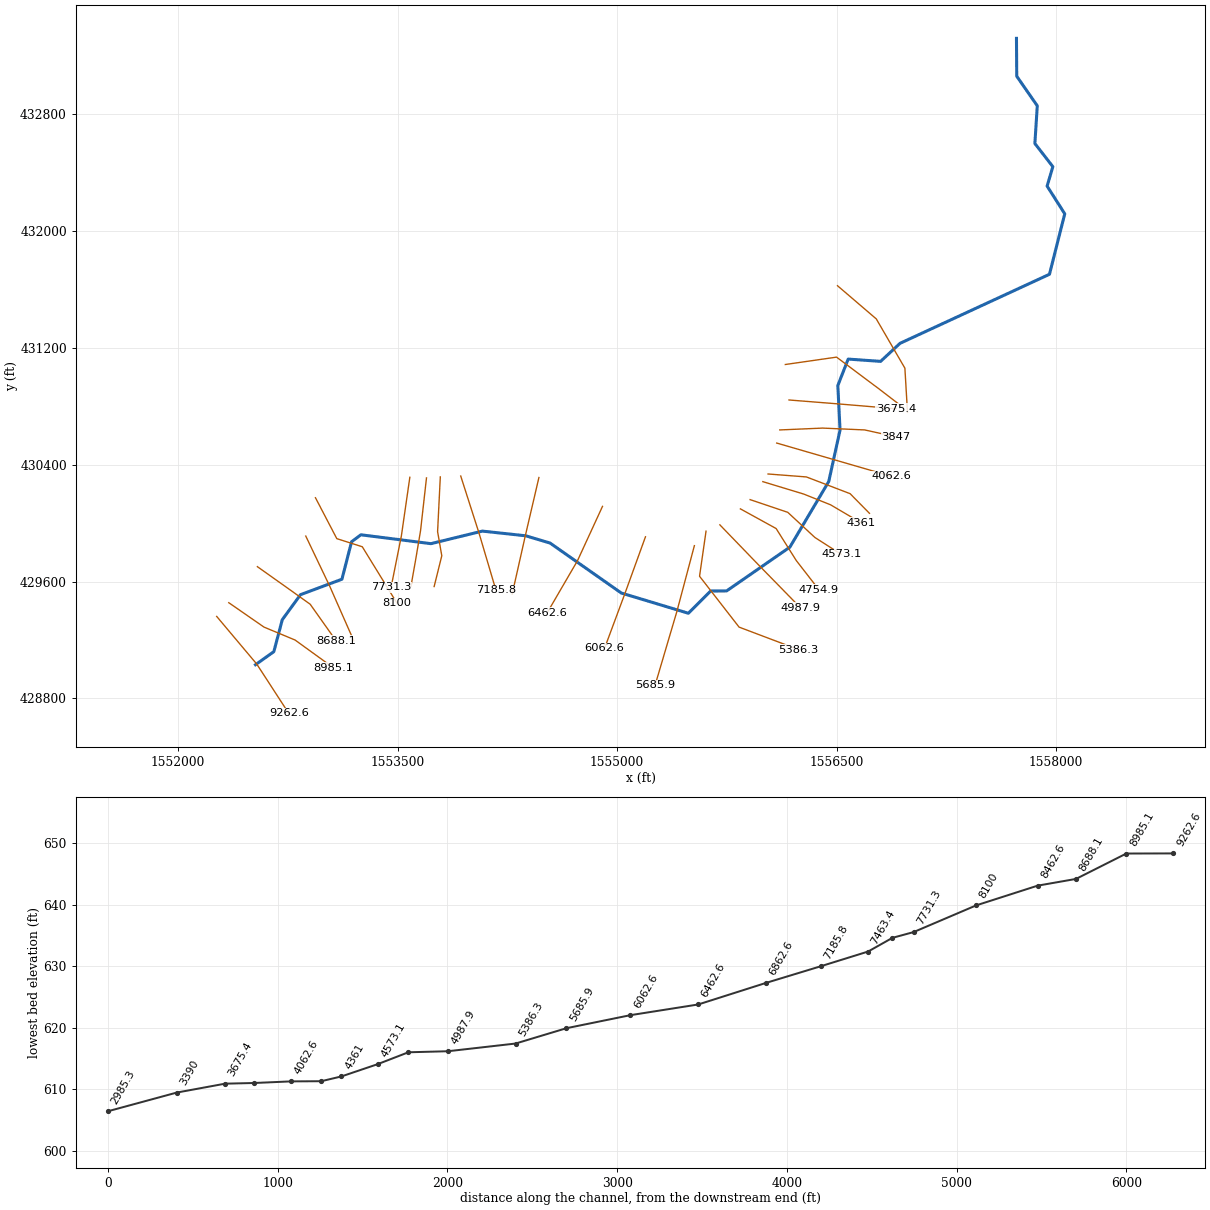
--- TWOMILECR.prj (project) ---

Proj Title=TWOMILECR
Current Plan=p01
Default Exp/Contr=0,0
English Units
Geom File=g01
Flow File=f01
Plan File=p01
BEGIN DESCRIPTION:
END DESCRIPTION:
DSS Export Rating Curves= 0
DSS Export Rating Curve Sorted= 0
DSS Export Volume Flow Curves= 0
DXF OffsetX= 0
DXF OffsetY= 0
DXF ScaleX= 0
DXF ScaleY= 0

--- TWOMILECR.p01 (plan) ---

Plan Title=Floodplain
Program Version=4.00
Geom File=g01
Flow File=f01
K Sum by GR=0
Std Step Tol=0.01
Critical Tol=0.01
Num of Std Step Trials=20
Max Error Tol=0.3
Flow Tol Ratio=0.001
Split Flow NTrial=30
Split Flow Tol=0.02
Split Flow Ratio=0.02
Log Output Level=0
Friction Slope Method=1
Unsteady Friction Slope Method=2
Unsteady Bridges Friction Slope Method=1
Global Log Level=0
CheckData=False
Run HTab=0
Run UNet=0
Run PostProcess=0
UNET Theta=0
UNET Theta Warmup=0
UNET ZTol=0
UNET ZSATol=0
UNET MxIter=0
UNET MaxInSteps=0
UNET DtIC=0
UNET DtMin=0
UNET MaxCRTS=0
UNET WFStab=0
UNET SFStab=0
UNET WFX=0
UNET SFX=0
UNET DSS MLevel=0
UNET DZMax Abort=0
UNET Convert EG Bridges=0
UNET Use Existing IB Tables=0
UNET Froude Limit=0
UNET Froude Power=0
Write IC File=0
Echo Input=False
Echo Output=False
Write Detailed=0

--- TWOMILECR.f01 (steady flow) ---

Flow Title=NFF Regression Equation
Program Version=4.00
Number of Profiles=1
Profile Names=P100yr
River Rch & RM=TWOMILECR,Main      ,9262.6
     352
River Rch & RM=TWOMILECR,Main      ,8985.1
     363
River Rch & RM=TWOMILECR,Main      ,8688.1
     394
River Rch & RM=TWOMILECR,Main      ,7185.8
     425
River Rch & RM=TWOMILECR,Main      ,5685.9
     464
River Rch & RM=TWOMILECR,Main      ,5386.3
     734
River Rch & RM=TWOMILECR,Main      ,2985.3
     792
Boundary for River Rch & Prof#=TWOMILECR,Main      ,1
Up Type=0
Dn Type=3
Dn Slope=0.005226

--- TWOMILECR.g01 (geometry) ---

Geom Title=USGS 10m DEM
Program Version=4.00

River Reach=TWOMILECR       ,Main
Reach XY= 30
     1552528.788      429030.173     1552654.394       429119.79
     1552711.982      429338.556     1552836.599       429510.06
     1553119.719      429615.782      1553185.57      429872.359
     1553249.293       429920.15     1553728.146      429859.423
     1554079.487      429945.411     1554375.638      429913.332
     1554542.157      429863.673     1555029.267      429521.239
     1555487.309      429382.872     1555640.043      429535.088
     1555748.446      429535.545      1556181.03      429835.449
     1556446.844      430284.768     1556524.108      430637.307
     1556508.969      430942.373     1556579.676      431123.519
     1556801.416       431107.82     1556934.077      431231.415
     1557955.415      431704.313     1558059.965      432118.465
     1557939.373      432308.241     1557978.483      432441.281
     1557855.679      432599.955     1557872.091      432858.073
     1557731.753      433060.792     1557729.895      433320.243

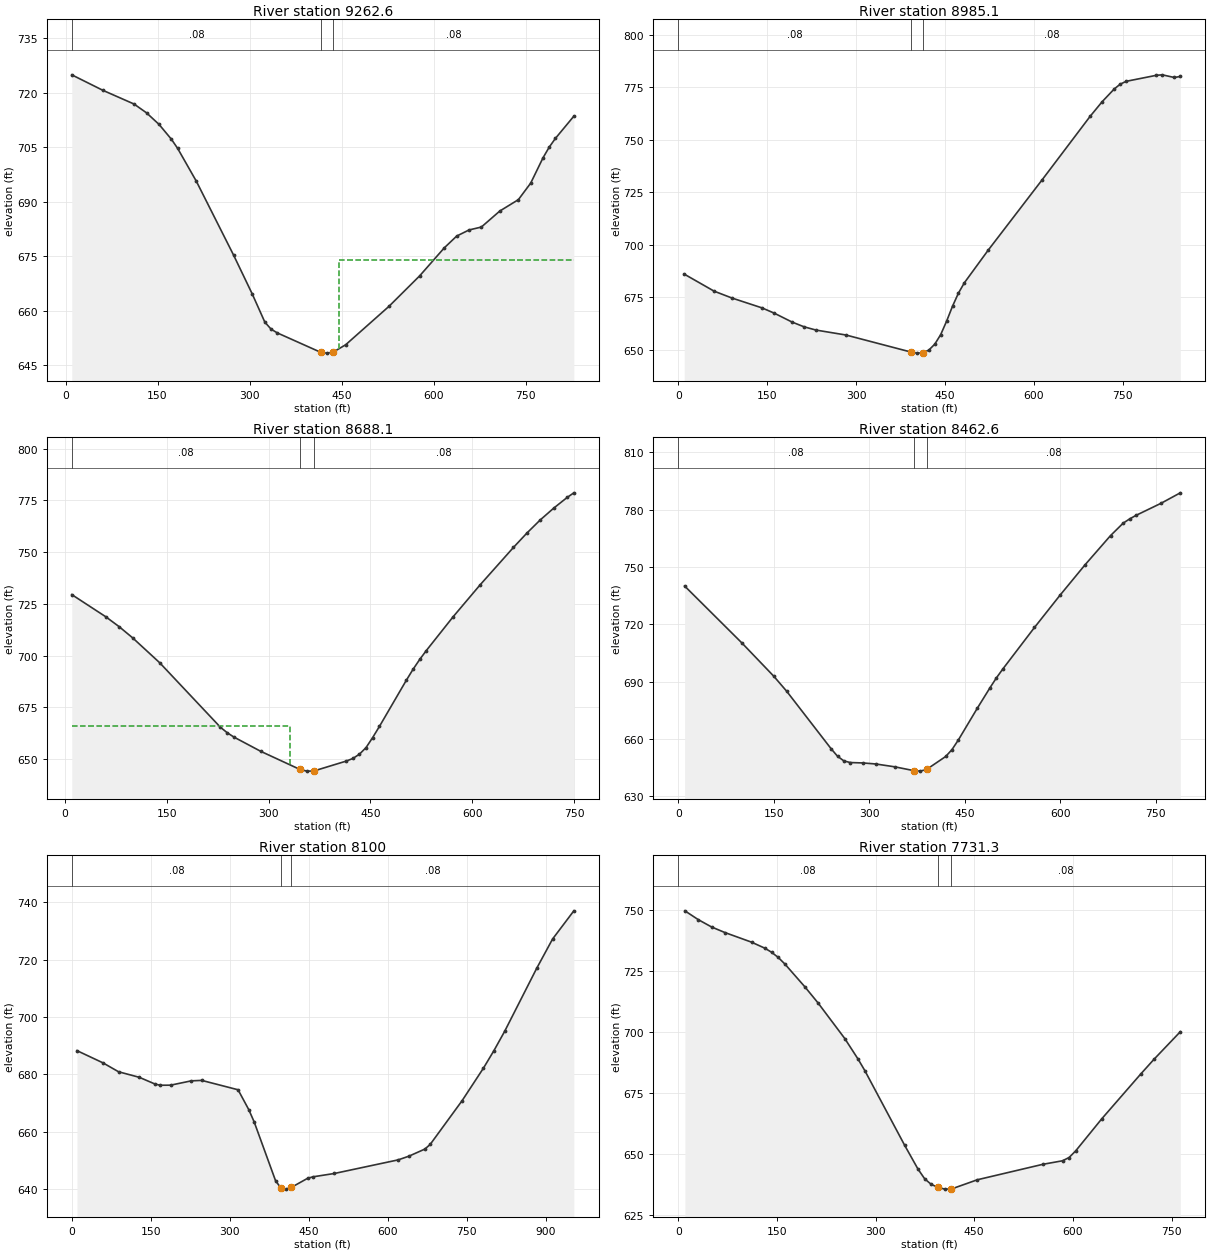
Type RM Length L Ch R = 1 ,9262.6  ,265.6,277.5,292.5
XS GIS Cut Line= 3
     1552263.777      429361.016     1552537.828      429034.447
     1552756.423      428697.084
#Sta/Elev= 30
    10.2  724.86    60.9   720.6   111.7  716.83     132  714.41   152.3  711.25
   172.6  707.14   182.7  704.64   213.2   695.6   274.1  675.22   304.5  664.53
   324.8  656.87     335  654.94   345.1  653.91   416.3  648.54   426.3  648.35
   436.3  648.64   456.5  650.65   526.8  661.17   577.1   669.6   617.3  677.31
   637.4  680.53   657.5  682.21   677.6  683.01   707.7  687.42   737.9  690.54
     758  695.09   778.1  702.06   788.1  704.96   798.2  707.37   828.3  713.49
#Mann= 3 , 0 , 0
    10.2     .08       0   416.3    .045       0   436.3     .08       0
#XS Ineff= 2 , 0
                          446.14          673.85
Permanent Ineff=
       F       F
Bank Sta=416.3,436.3
XS Rating Curve= 0 ,0
Exp/Cntr=0.3,0.1

Type RM Length L Ch R = 1 ,8985.1  ,304.2,297.1,290.7
XS GIS Cut Line= 4
     1552346.497      429454.936     1552587.267      429287.867
     1552799.343      429199.502     1553062.082      429009.007
#Sta/Elev= 30
    10.1  686.01    60.6  677.87    90.9  674.58   141.5  669.89   161.7  667.43
     192  663.16   212.2  660.89   232.4  659.33     283  656.97   392.9  648.83
   402.9  648.33   412.9  648.45   422.9  649.78   432.9  652.59   442.9  657.14
   452.9  663.57   462.9  670.71   472.9  676.96   482.8  681.84   522.8  697.32
   614.1  730.96   695.2  761.27   715.5  768.24   735.8  774.29   745.9  776.58
   756.1  777.94   806.8   780.8   816.9  781.03   837.2  779.76   847.3  780.25
#Mann= 3 , 0 , 0
       0     .08       0   392.9    .045       0   412.9     .08       0
Bank Sta=392.9,412.9
XS Rating Curve= 0 ,0
Exp/Cntr=0.3,0.1

Type RM Length L Ch R = 1 ,8688.1  ,237.1,225.5,209.1
XS GIS Cut Line= 4
     1552541.822       429701.92     1552769.046      429540.339
     1552902.856      429444.399     1553079.586      429194.453
#Sta/Elev= 30
      10  729.52    59.7  718.89    79.7  714.04    99.6  708.63   139.4  696.62
     229   665.4     239  662.75   248.9  660.65   288.5  653.75   346.3  644.99
   356.3   644.2   366.3  644.24   414.4  649.06   424.1  650.32   433.8   652.4
   443.5  655.58   453.3  660.45   463.2   665.8   502.7  688.04   512.6  693.34
   522.5  698.15   532.3  702.48   571.8  718.81   611.3  734.14   660.7  752.33
   680.5  759.27   700.2  765.63     720  771.31   739.7  776.45   749.6   778.7
#Mann= 3 , 0 , 0
      10     .08       0   346.3    .045       0   366.3     .08       0
#XS Ineff= 2 , 0
          330.82  665.81
Permanent Ineff=
       F       F
Bank Sta=346.3,366.3
XS Rating Curve= 0 ,0
Exp/Cntr=0.3,0.1

Type RM Length L Ch R = 1 ,8462.6  ,342.1,362.6,384
XS GIS Cut Line= 3
      1552872.56      429911.471     1553036.217      429568.146
     1553200.773      429194.453
#Sta/Elev= 30
      10  740.05   100.1  710.19   150.1   692.8   170.2     685   240.2  654.81
   250.2  650.92   260.2  648.46   270.2  647.61   290.3  647.39   310.3  646.85
   340.3  645.36   370.3  643.35   380.3  643.11   390.3  644.03   420.2  650.79
   430.1  654.42   440.1  659.46     470  676.15   489.9  686.85   499.8  691.93
   509.8  696.55   559.6  718.32   599.4  735.08   639.3  751.24   679.1  766.44
     699  772.97     709  775.14   718.9  776.99   758.8  783.42   788.7  788.83
#Mann= 3 , 0 , 0
       0     .08       0   370.3    .045       0   390.3     .08       0
Bank Sta=370.3,390.3
XS Rating Curve= 0 ,0
Exp/Cntr=0.3,0.1

Type RM Length L Ch R = 1 ,8100    ,405,368.7,331.3
XS GIS Cut Line= 4
     1552938.868      430173.846     1553084.636      429893.798
     1553258.841      429838.255     1553496.624      429450.792
#Sta/Elev= 30
     9.9  688.21    59.2  683.95    88.8  680.84   128.3   678.9   157.9  676.57
   167.7  676.14   187.5  676.16   226.9  677.67   246.7  677.83   315.7  674.56
     336  667.64   346.2  663.39   386.8  642.88   397.1  640.26   407.1   639.9
   417.1  640.53   447.8  643.68   457.9  644.19   498.6  645.36   619.8  650.11
     640  651.39   670.3  653.87   680.4  655.48     741  670.74   781.4  682.06
   801.6  688.25   821.8  694.93   882.5  716.87   912.8  727.14   953.2  736.98
#Mann= 3 , 0 , 0
       0     .08       0   397.1    .045       0   417.1     .08       0
Bank Sta=397.1,417.1
XS Rating Curve= 0 ,0
Exp/Cntr=0.3,0.1

Type RM Length L Ch R = 1 ,7731.3  ,112.6,124.2,136.6
XS GIS Cut Line= 3
     1553583.849      430314.124     1553526.123       429913.17
     1553455.856      429561.887
#Sta/Elev= 30
    10.1  749.55    30.4  745.95    50.6  742.95    70.9  740.66   111.4  736.72
   131.7  734.24   141.8   732.6   151.9  730.49     162   727.8   192.4  718.46
   212.7  711.77   253.2  697.24   273.4  688.82   283.6  684.14   344.3  653.48
   364.6  643.72   374.7  639.78   384.8  637.46   395.1   636.3   405.1  635.56
   415.1   635.6   454.8   639.4   554.4  645.73   584.2  647.17   594.2  648.51
   604.1  651.18   643.9  664.37   703.6  682.85   723.5   688.8   763.3  700.03
#Mann= 3 , 0 , 0
       0     .08       0   395.1    .045       0   415.1     .08       0
Bank Sta=395.1,415.1
XS Rating Curve= 0 ,0
Exp/Cntr=0.3,0.1

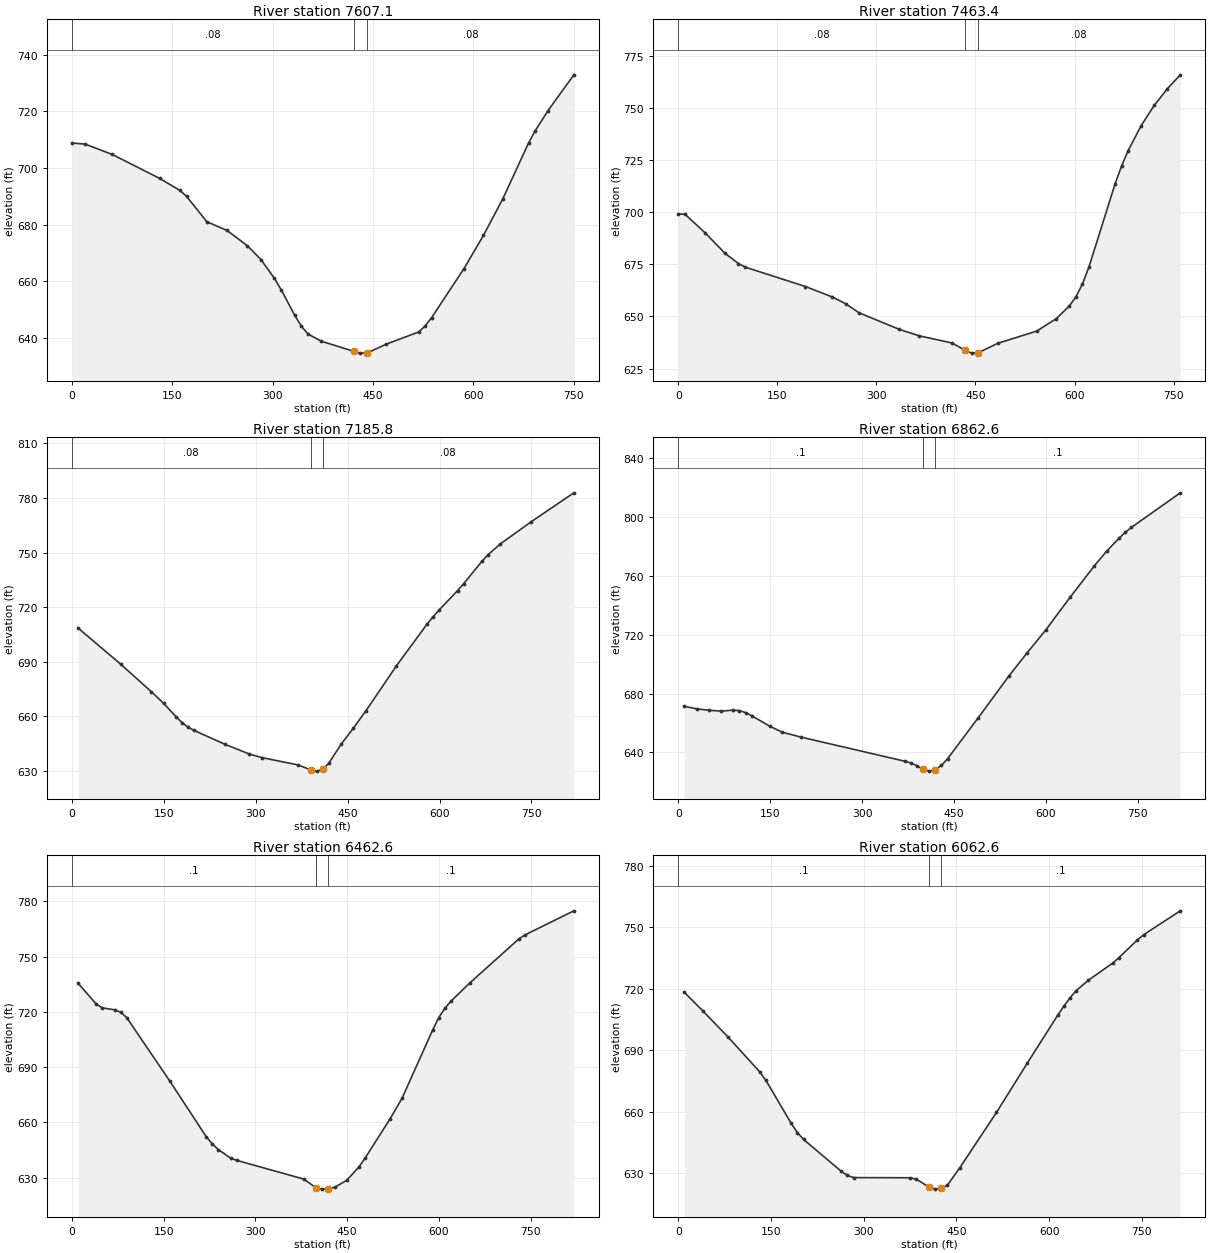
Type RM Length L Ch R = 1 ,7607.1  ,135.2,143.7,152.3
XS GIS Cut Line= 4
     1553697.615      430309.711     1553657.122      429948.649
     1553623.378      429747.871     1553591.321       429567.34
#Sta/Elev= 30
       0  708.84    20.2  708.42    60.6  704.77   131.2  696.34   161.5   692.1
   171.6  689.99   201.8  681.02   232.1  677.94   262.4  672.55   282.6  667.69
   302.8  661.05   312.9  657.01     333  648.07   343.1  644.13   353.2  641.36
     373  638.83   421.2  635.28   431.2  634.63   441.2  634.65     470  637.81
   518.4   642.1   528.1  644.22   537.8  647.18   586.2   664.5   615.2   676.2
   644.1   689.1   682.7  708.87   692.4  713.08   711.7  720.25   750.3   732.9
#Mann= 3 , 0 , 0
       0     .08       0   421.2    .045       0   441.2     .08       0
Bank Sta=421.2,441.2
XS Rating Curve= 0 ,0
Exp/Cntr=0.3,0.1

Type RM Length L Ch R = 1 ,7463.4  ,274.1,277.6,280.7
XS GIS Cut Line= 4
     1553792.098       430316.46     1553773.539        429941.9
     1553802.222      429776.554     1553749.918      429565.653
#Sta/Elev= 30
       0  699.02    10.1  699.02    40.5  690.12    70.9  680.22    91.2  675.34
   101.4  673.61   192.6  664.33   233.1  659.33   253.4   656.1   273.7  651.73
   334.5  643.81   364.9  640.68   414.5  637.27   434.1  633.82   444.1   632.4
   454.1  632.57   483.6  637.09   542.8  642.97   572.5  648.96   592.2  655.06
   602.1  659.39     612  665.55   621.8  673.71   661.4  713.57   671.2  722.09
   681.1  729.46   700.9  741.47   720.6  751.14   740.4  759.09   760.1  765.79
#Mann= 3 , 0 , 0
       0     .08       0   434.1    .045       0   454.1     .08       0
Bank Sta=434.1,454.1
XS Rating Curve= 0 ,0
Exp/Cntr=0.3,0.1

Type RM Length L Ch R = 1 ,7185.8  ,336.8,323.2,310.2
XS GIS Cut Line= 3
     1553931.684      430322.417     1554056.446      429932.407
     1554172.765      429539.652
#Sta/Elev= 30
      10  708.65    79.9  688.69   129.8  673.62   149.8  667.26   169.8  659.98
   179.8  656.66   189.8  654.13   199.7  652.32   249.7  644.77   289.6  639.43
   309.6  637.47   369.5  633.41   389.5  630.74   399.5  630.02   409.5  630.98
   419.5  634.44   439.5  644.81   459.4   653.6   479.4   662.9   529.4  687.67
   579.3  710.56   589.3   714.7   599.3  718.43   629.3  729.04   639.3  732.87
   669.2  745.19   679.2  748.84   699.2  754.72   749.2   766.8   819.1  782.75
#Mann= 3 , 0 , 0
       0     .08       0   389.5    .045       0   409.5     .08       0
Bank Sta=389.5,409.5
XS Rating Curve= 0 ,0
Exp/Cntr=0.3,0.1

Type RM Length L Ch R = 1 ,6862.6  ,405.1,400,392.3
XS GIS Cut Line= 3
     1554466.062      430312.394     1554373.125       429913.81
     1554283.269      429513.977
#Sta/Elev= 30
      10  671.27    29.9  669.63    49.9  668.63    69.9  668.08    89.8  668.69
    99.8  668.41   109.8  667.02   119.8  664.91   149.7  657.74   169.7  653.76
   199.6  650.47   369.3  634.07   379.3   632.9   389.3  631.06   399.3  628.44
   409.3  627.31   419.3   628.2   429.3  631.14   439.3   635.7   489.2  663.41
   539.2  691.77   569.2  707.65   599.2  722.93   639.2  745.29   679.1  766.84
   699.1  776.72   719.1  785.45   729.1  789.35   739.1  792.74   819.1  816.27
#Mann= 3 , 0 , 0
       0      .1       0   399.3    .045       0   419.3      .1       0
Bank Sta=399.3,419.3
XS Rating Curve= 0 ,0
Exp/Cntr=0.3,0.1

Type RM Length L Ch R = 1 ,6462.6  ,398,400,404.2
XS GIS Cut Line= 3
     1554900.615      430114.719     1554729.774      429742.861
     1554523.259      429387.369
#Sta/Elev= 30
      10  735.64    39.9  724.26    49.9  722.15    69.9  721.11    79.8  719.83
    89.8  716.88   159.7  682.67   219.6  652.31   229.6  648.34   239.5  645.27
   259.5  640.63   269.5   639.4   379.3  629.23   399.2  624.44   409.2   623.8
   419.2  623.99   429.3  624.74   449.3   628.6   469.4  635.92   479.4  640.72
   519.5  661.63   539.6   673.1   589.7  710.21   599.7  716.93   609.8  722.06
   619.8  725.89   649.9  735.57   730.1  759.47   740.1  761.69   820.3  774.82
#Mann= 3 , 0 , 0
       0      .1       0   399.2    .045       0   419.2      .1       0
Bank Sta=399.2,419.2
XS Rating Curve= 0 ,0
Exp/Cntr=0.3,0.1

Type RM Length L Ch R = 1 ,6062.6  ,374.5,376.7,378.5
XS GIS Cut Line= 3
     1555194.328      429906.588     1555052.998      429515.657
     1554915.053      429143.959
#Sta/Elev= 30
    10.1  718.23    40.6  708.99    81.1  696.27   131.8  679.42   141.9  675.21
   182.5  654.35   192.6  649.74   202.8  646.34   263.6  630.82   273.7  628.73
   283.9   627.7   375.1  627.61   385.3  626.91   405.7  623.03   415.7  622.06
   425.7  622.38   435.5  624.03   455.3  632.42   514.8  659.55   564.4  683.55
   613.9  707.11   623.8  711.54   633.8  715.61   643.7  719.14   663.5   724.2
   703.1  732.65     713  735.29   742.8  743.93   752.7  746.42   812.2  758.15
#Mann= 3 , 0 , 0
       0      .1       0   405.7    .045       0   425.7      .1       0
Bank Sta=405.7,425.7
XS Rating Curve= 0 ,0
Exp/Cntr=0.3,0.1

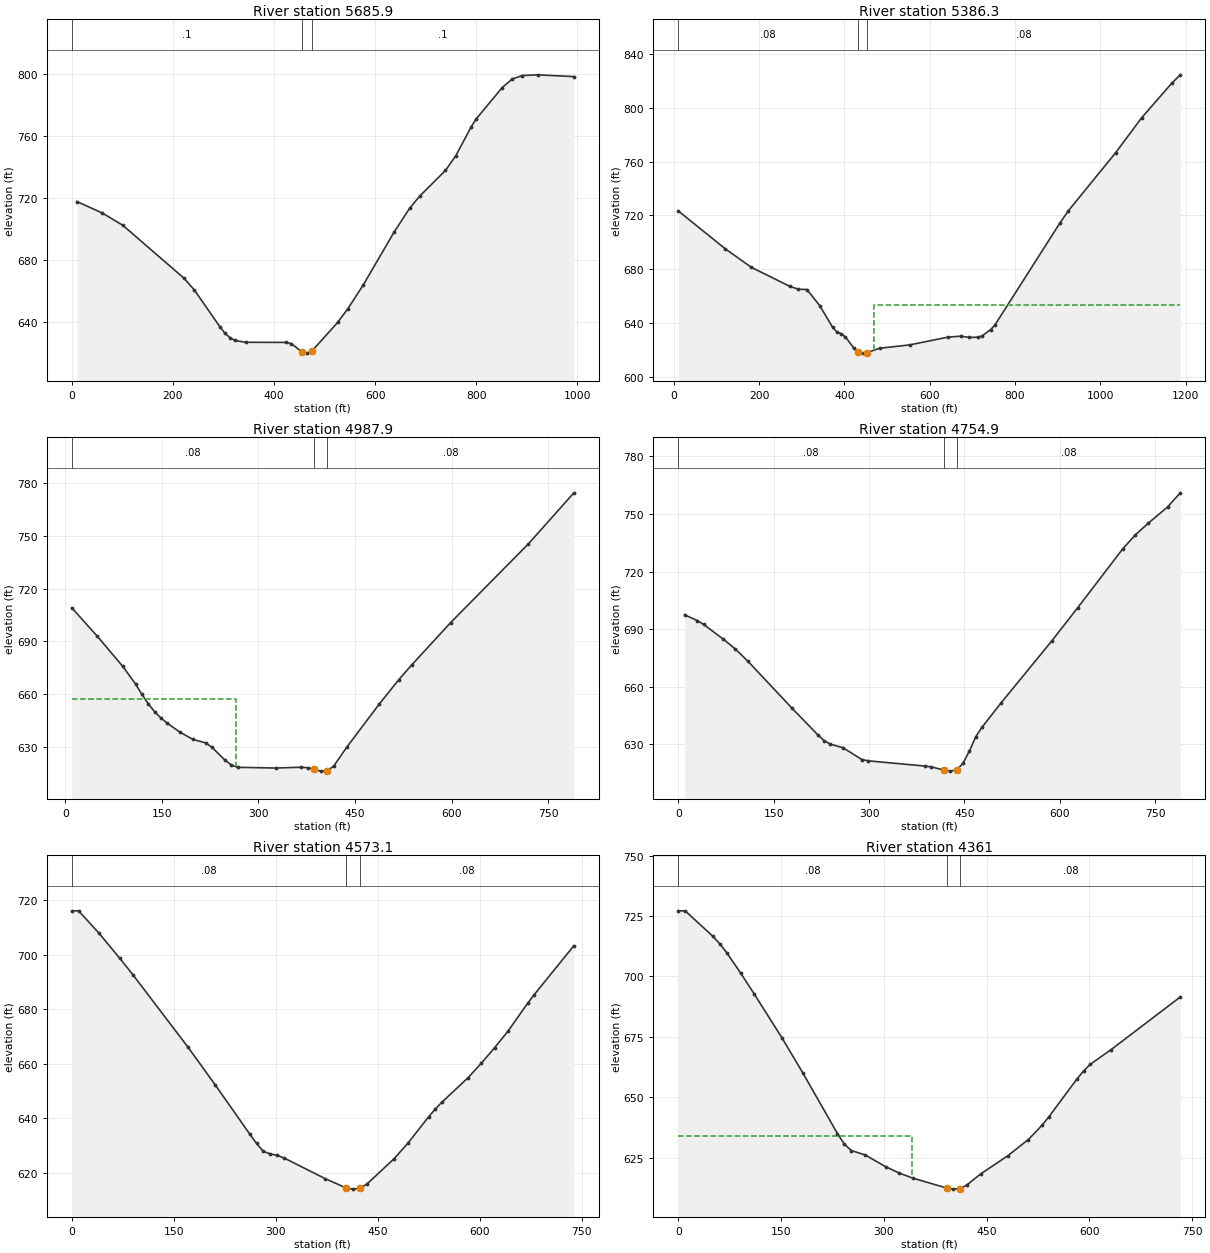
Type RM Length L Ch R = 1 ,5685.9  ,275.3,299.6,327
XS GIS Cut Line= 3
     1555528.558      429845.829     1555409.389      429396.541
     1555259.992      428889.909
#Sta/Elev= 30
    10.1  717.66    60.6  710.25     101  702.35   222.3  668.15   242.5  660.61
     293  636.91   303.1  632.73   313.3  629.74   323.4  628.11   343.6  626.94
   424.4  626.84   434.5  626.05   454.8  620.81   464.8  619.94   474.8  621.25
   525.8  639.71   546.1   648.6   576.6  663.95   637.5  697.97     668   713.2
   688.3  721.21   739.1  737.73   759.4  747.16   789.9  765.75     800  771.01
   850.8  790.96   871.1  796.69   891.4  798.93   921.9  799.37     993  798.22
#Mann= 3 , 0 , 0
       0      .1       0   454.8    .045       0   474.8      .1       0
Bank Sta=454.8,474.8
XS Rating Curve= 0 ,0
Exp/Cntr=0.3,0.1

Type RM Length L Ch R = 1 ,5386.3  ,396.2,398.4,398.1
XS GIS Cut Line= 4
      1555608.26      429945.157     1555563.905      429636.278
     1555834.049      429287.867     1556240.528       429133.86
#Sta/Elev= 30
    10.1  723.43   120.8  695.08   181.2  681.46   271.8  667.19   291.9  665.05
     312  664.83   342.1  652.74   372.2  636.67   382.2  633.22   392.2  631.93
   402.2  629.52   422.3  621.08   432.3  618.31   442.3  617.45   452.3  617.79
   482.4  621.09   552.5  623.56   642.7  629.37   672.8   630.1   692.8  629.13
   712.8  629.31   722.9   630.3   742.9     635   752.9  638.44   904.6  714.07
   924.8   723.4    1036  766.79  1096.6  792.65  1167.4  818.53  1187.6  824.79
#Mann= 3 , 0 , 0
    10.1     .08       0   432.3    .045       0   452.3     .08       0
#XS Ineff= 2 , 0
                          469.65          653.37
Permanent Ineff=
       F       F
Bank Sta=432.3,452.3
XS Rating Curve= 0 ,0
Exp/Cntr=0.3,0.1

Type RM Length L Ch R = 1 ,4987.9  ,238.3,233,227.7
XS GIS Cut Line= 3
     1555702.743      429988.248     1555970.992      429709.891
     1556252.886      429421.263
#Sta/Elev= 30
     9.9  709.09    49.6  692.89    89.2  675.74     109  665.73   118.9  659.82
   128.9  654.46   138.8  649.92   148.7  646.34   158.6  643.37   178.4  638.25
   198.2  634.24   218.1  632.24     228  629.66   247.8  622.51   257.7  619.71
   267.6  618.37   327.1  617.97   366.8  618.41   376.7  618.13   386.7  617.25
   396.7   616.2   406.7  616.41   416.8  619.02     437  629.73   487.4  654.23
   517.7  668.07   537.9  676.52   598.4  700.62   719.4  745.44     790  774.47
#Mann= 3 , 0 , 0
     9.9     .08       0   386.7    .045       0   406.7     .08       0
#XS Ineff= 2 , 0
           264.7  657.44
Permanent Ineff=
       F       F
Bank Sta=386.7,406.7
XS Rating Curve= 0 ,0
Exp/Cntr=0.3,0.1

Type RM Length L Ch R = 1 ,4754.9  ,165.7,181.8,198
XS GIS Cut Line= 4
     1555843.085      430097.715     1556087.282      429962.986
     1556224.818      429744.051     1556379.195      429544.765
#Sta/Elev= 30
      10  697.43    29.9  694.49    39.8  692.48    69.7  685.07    89.6   679.7
   109.6  673.27   179.3  648.67   219.1  635.07   229.1  631.98   239.1  630.09
     259  628.22   288.8  622.06   298.8  621.39   388.3  618.66   398.2  618.22
   418.1  616.58   428.1  616.03   438.1  616.74   447.9  620.14   457.9  626.53
   467.8  633.91   477.8  638.95   507.6  651.55   587.9  684.06   628.2  701.17
   698.8  731.77     719  739.15   739.1  745.16   769.4  753.63   789.5     761
#Mann= 3 , 0 , 0
       0     .08       0   418.1    .045       0   438.1     .08       0
Bank Sta=418.1,438.1
XS Rating Curve= 0 ,0
Exp/Cntr=0.3,0.1

Type RM Length L Ch R = 1 ,4573.1  ,202.7,212.2,221.7
XS GIS Cut Line= 4
     1555909.463      430160.998     1556166.928      430073.914
     1556352.455      429901.639     1556532.302      429786.159
#Sta/Elev= 30
       0  716.09    10.1  716.09    40.3  707.82    70.5  698.74    90.6  692.46
   171.1  666.09   211.4  652.18   261.7  634.32   271.8  630.87   281.9   627.9
     292  627.02   302.2  626.47   312.3  625.52   373.1   617.9   403.6  614.53
   413.6  614.09   423.6  614.44   433.8  615.85   474.3  625.25   494.6  630.93
     525  640.59   534.7  643.39   544.4   645.9   583.3  654.99   602.7  660.27
   622.1  665.92   641.6   671.9   670.7  682.21   680.4  685.37   738.7  703.31
#Mann= 3 , 0 , 0
       0     .08       0   403.6    .045       0   423.6     .08       0
Bank Sta=403.6,423.6
XS Rating Curve= 0 ,0
Exp/Cntr=0.3,0.1

Type RM Length L Ch R = 1 ,4361    ,118.7,119.1,119.4
XS GIS Cut Line= 4
     1555996.547      430284.051     1556276.729       430198.86
     1556460.363      430125.028     1556668.607      430001.975
#Sta/Elev= 30
       0  727.14    10.1  727.14    50.5  716.63    60.6   713.5    70.7  709.88
    90.9   701.5   111.1  692.68   151.5  674.58   181.8  660.16   232.3  635.08
   242.4  630.72   252.5  628.07   272.7  626.25   302.7  621.38   322.5  618.74
   342.3  616.66   391.7  612.57   401.7  612.11   411.7  612.32   421.5  613.89
   441.3  618.38   480.9  625.89   510.9  632.59   531.1  638.55   541.2  642.11
   581.5   657.5   591.6  660.97   601.6  663.77   631.9  669.82   732.7  691.54
#Mann= 3 , 0 , 0
       0     .08       0   391.7    .045       0   411.7     .08       0
#XS Ineff= 2 , 0
          341.38  633.93
Permanent Ineff=
       F       F
Bank Sta=391.7,411.7
XS Rating Curve= 0 ,0
Exp/Cntr=0.3,0.1

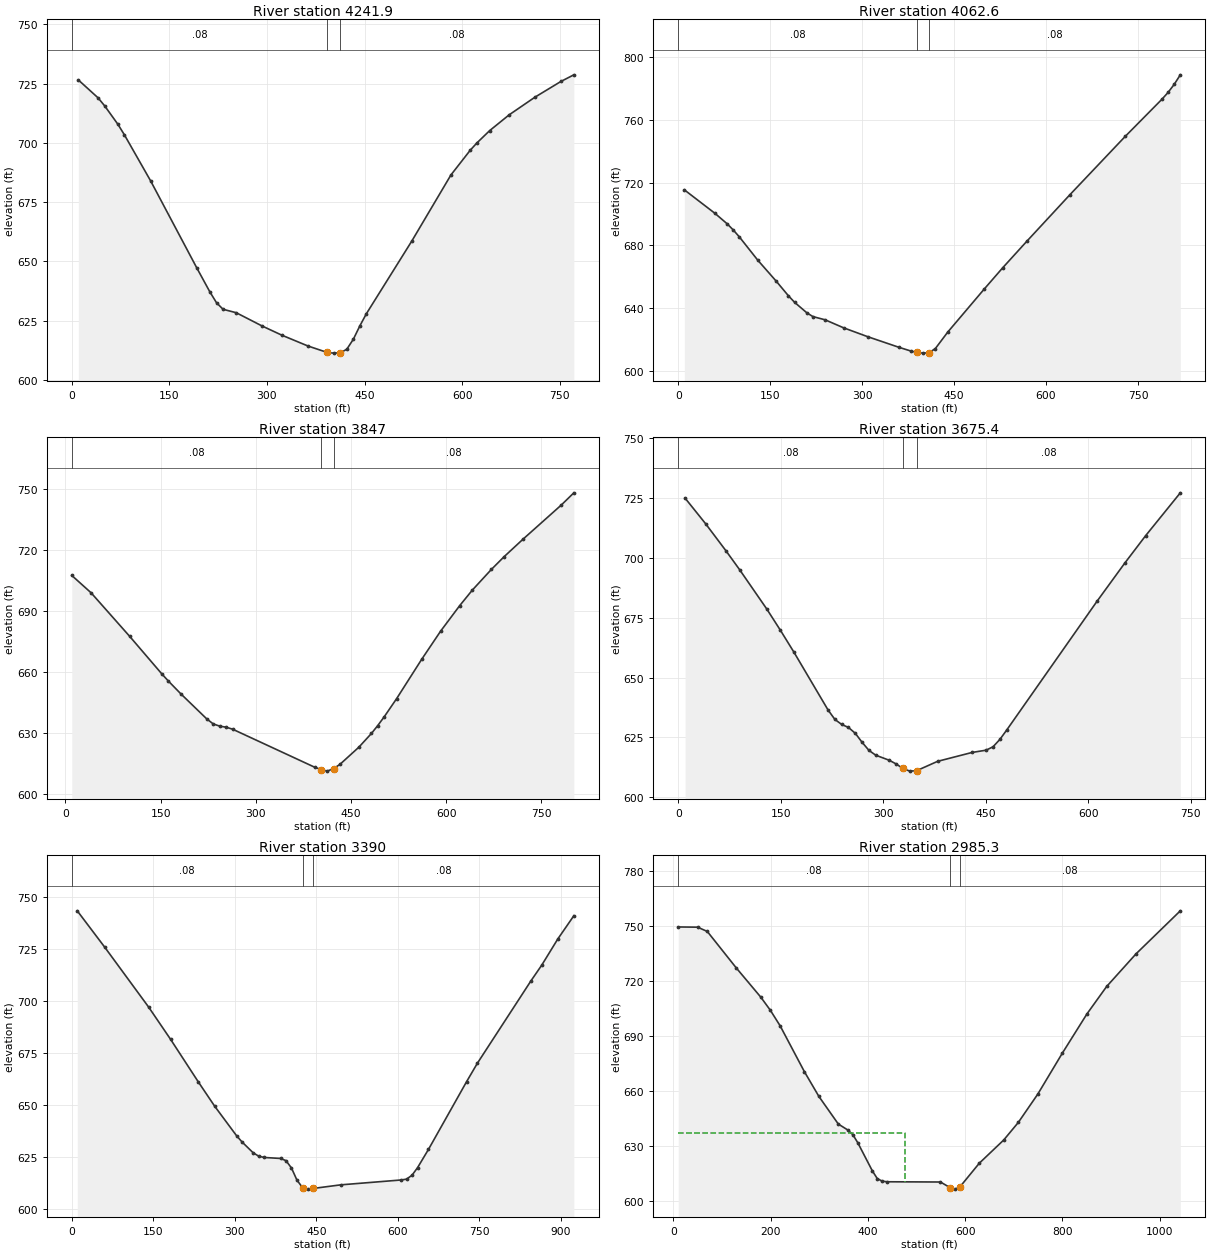
Type RM Length L Ch R = 1 ,4241.9  ,177.2,179.3,181.4
XS GIS Cut Line= 4
     1556032.025      430336.593     1556294.147      430316.369
     1556592.796      430201.849      1556725.28       430067.12
#Sta/Elev= 30
    10.1  726.54    40.4     719    50.6   715.6    70.8  707.88    80.9  703.39
   121.3  683.93   192.1   647.3   212.3  637.14   222.5  632.57   232.6  629.81
   252.8  628.37   292.9  622.73   322.9   618.9   362.9  614.35   392.8   611.6
   402.8  611.33   412.8  611.44   422.8     613   432.8  617.19   442.8  622.83
   452.8  627.94   522.8  658.67   582.8  686.48   612.6  696.95   622.5  699.92
   642.4  705.19   672.3  711.83     712  719.29   751.8   725.9   771.7   728.7
#Mann= 3 , 0 , 0
       0     .08       0   392.8    .045       0   412.8     .08       0
Bank Sta=392.8,412.8
XS Rating Curve= 0 ,0
Exp/Cntr=0.3,0.1

Type RM Length L Ch R = 1 ,4062.6  ,209.7,215.7,221.6
XS GIS Cut Line= 3
     1556091.215      430548.479     1556484.435      430434.162
     1556877.655      430319.846
#Sta/Elev= 30
      10  715.43    59.9  700.45    79.9  693.74    89.9  689.79    99.9  685.33
   129.8  670.55   159.8  657.21   179.8  647.84   189.8  643.71   209.7  637.04
   219.7   634.6   239.7  632.54   269.7  627.45   309.6  621.71   359.6  615.07
   379.5  612.64   389.5  611.74   399.5   611.3   409.5  611.63   419.5  614.25
   439.5  624.65   499.4  652.28   529.4  665.78   569.3  682.93   639.2  712.45
   729.1   749.5     789   773.2     799  777.54     809  782.68     819  788.79
#Mann= 3 , 0 , 0
       0     .08       0   389.5    .045       0   409.5     .08       0
Bank Sta=389.5,409.5
XS Rating Curve= 0 ,0
Exp/Cntr=0.3,0.1

Type RM Length L Ch R = 1 ,3847    ,172.5,171.5,170.4
XS GIS Cut Line= 4
     1556112.083      430638.273     1556405.581      430650.897
     1556692.767      430638.273     1556907.368      430590.935
#Sta/Elev= 30
    10.1  707.28    40.5  698.76   101.3  677.33   151.9  658.88   162.1   655.4
   182.3  648.93   222.9  636.68     233  634.25   243.1  633.17   253.2  632.65
   263.4  631.67   392.9  612.94   402.7  611.83  412.62  611.04   422.7  612.33
   432.5  614.35   462.3   622.8   482.1  629.55     492  633.41   501.9  637.59
   521.8  646.68   561.4  666.07   591.2  679.91   621.2  692.43   641.2  700.11
   671.1  710.24   691.1  716.49   721.1  725.16     781  741.84     801  747.91
#Mann= 3 , 0 , 0
    10.1     .08       0   402.7    .045       0   422.7     .08       0
Bank Sta=402.7,422.7
XS Rating Curve= 0 ,0
Exp/Cntr=0.3,0.1

Type RM Length L Ch R = 1 ,3675.4  ,299.5,285.4,271.4
XS GIS Cut Line= 3
     1556175.201      430843.406     1556512.932      430816.536
     1556907.368      430783.444
#Sta/Elev= 30
      10  724.92    39.9  714.28    69.8  702.94    89.7  695.08   129.5  678.64
   149.5  669.74   169.4  660.54   219.2  636.46   229.2  632.52   239.2  630.41
   249.1  629.16   259.1  626.71     269  622.97     279   619.6     289  617.58
   308.9  615.45   318.9  613.91   328.8  612.03   338.8  610.93   348.8  611.11
   379.4  615.01   430.1  618.74   450.4  619.67   460.6   621.1   470.7   624.2
   480.9  628.21   612.8  681.88   653.4  697.81   683.9  709.25   734.6  727.13
#Mann= 3 , 0 , 0
       0     .08       0   328.8    .045       0   348.8     .08       0
Bank Sta=328.8,348.8
XS Rating Curve= 0 ,0
Exp/Cntr=0.3,0.1

Type RM Length L Ch R = 1 ,3390    ,414.7,404.7,394.8
XS GIS Cut Line= 4
     1556149.954       431086.41     1556500.258      431136.904
       1556790.6      430919.148     1556954.706      430792.912
#Sta/Elev= 30
    10.1  743.33    60.7  725.82   141.6  696.98     182  681.46   232.6  661.15
   262.9  649.39   303.4  635.11   313.5  632.12   333.7  626.98   343.8  625.36
   353.9  624.71   384.2  624.23   394.2  623.18   404.3  619.64   414.4  613.79
   424.6  610.23   434.6  609.48   444.6  609.82   495.1  611.54     606  613.88
     616  614.28   626.1  616.16   636.2  619.76   656.4  628.59   726.7  661.24
   746.4  670.03     845  709.66   864.7  717.15   894.3  729.76   923.9  740.97
#Mann= 3 , 0 , 0
       0     .08       0   424.6    .045       0   444.6     .08       0
Bank Sta=424.6,444.6
XS Rating Curve= 0 ,0
Exp/Cntr=0.3,0.1

Type RM Length L Ch R = 1 ,2985.3  ,2964.2,2985.3,3006.2
XS GIS Cut Line= 4
      1556506.57      431626.068     1556771.664      431398.843
      1556967.33      431061.163     1556985.167      430758.578
#Sta/Elev= 30
      10  749.31    49.9  749.19    69.8  746.85   129.7  726.87   179.6  711.12
   199.5  703.89   219.5  695.46   269.3  670.52   299.3  656.94   339.2  641.91
   359.2  638.59   369.2  636.07   379.2  631.75   409.2  616.39   419.2  612.24
   429.2   610.8   439.2  610.46   549.3  610.33   569.3  607.22   579.3  606.45
   589.3  607.68   629.3  620.62   679.4  633.23   709.4  642.81   749.5  658.26
     800  680.59   850.6  701.96     891  716.87   951.6   734.7  1042.5   758.1
#Mann= 3 , 0 , 0
      10     .08       0   569.3    .045       0   589.3     .08       0
#XS Ineff= 2 , 0
          477.16  637.04
Permanent Ineff=
       F       F
Bank Sta=569.3,589.3
XS Rating Curve= 0 ,0
Exp/Cntr=0.3,0.1

Chan Stop Cuts=-1
Use User Specified Reach Order=0